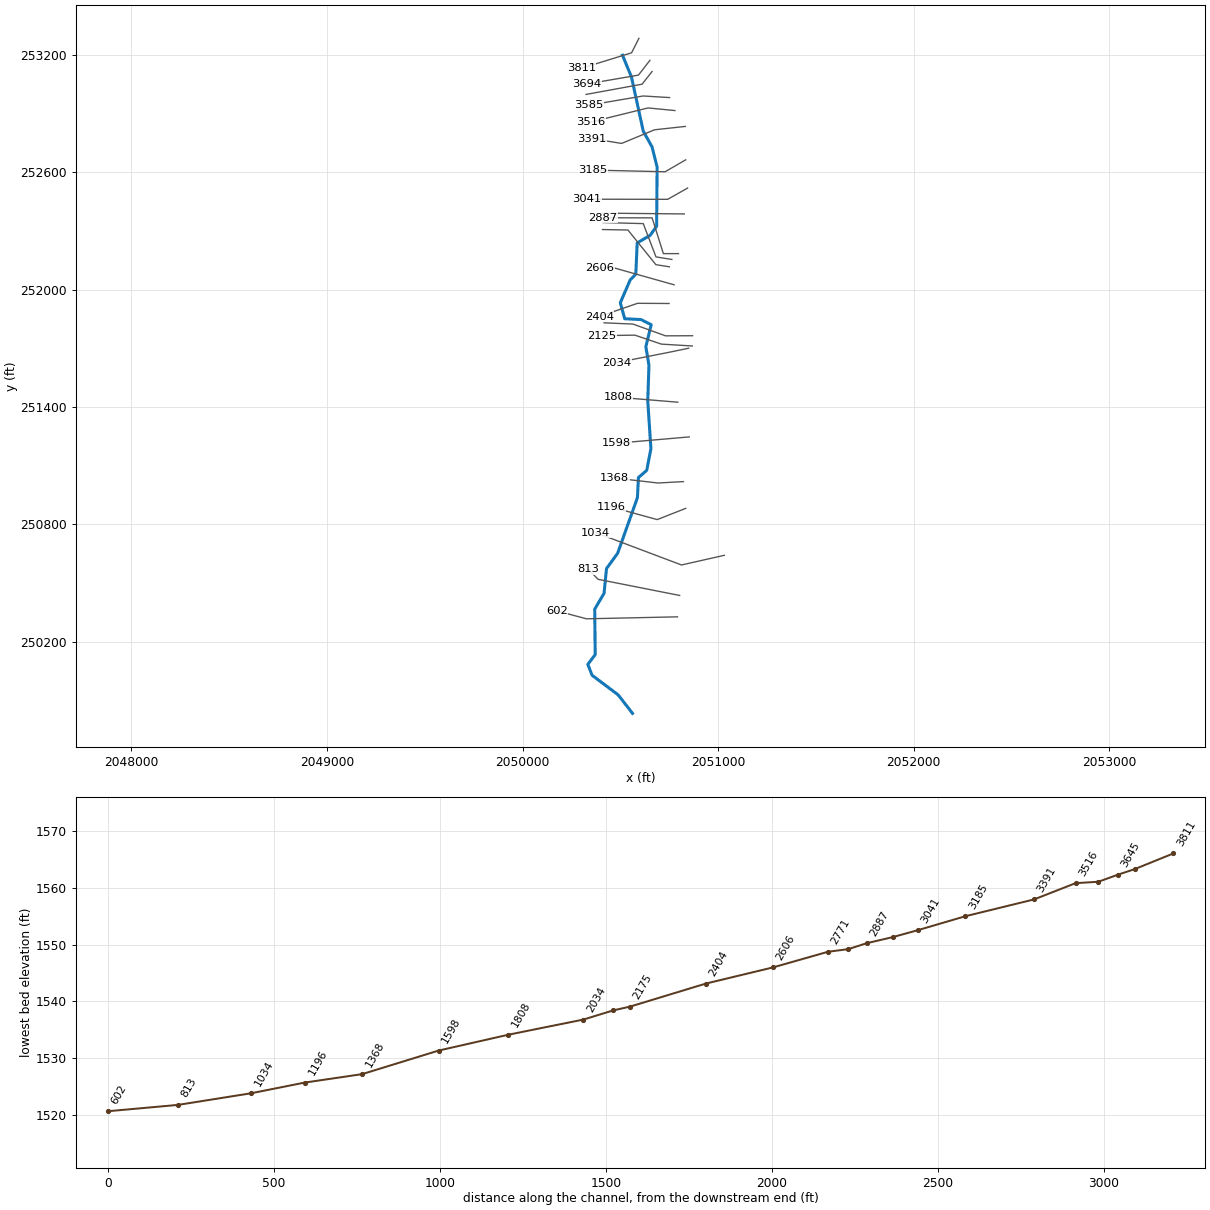
--- BUGGYBR_A.prj (project) ---

Proj Title=BUGGYBR_A
Current Plan=p01
Default Exp/Contr=0,0
English Units
Geom File=g01
Flow File=f01
Plan File=p01
BEGIN DESCRIPTION:
Stream Name: Buggy Branch
Flood Zone: Approximate
Summers County, West Virginia
HEC-RAS Version: 5.0.7
Hydrology Method:
 gage-weighting
Model Notes:
KWSEL tie in with BUGGGYBR_AE, shared XS with BUGGYBR_AE
END DESCRIPTION:
DSS Export Rating Curves= 0
DSS Export Rating Curve Sorted= 0
DSS Export Volume Flow Curves= 0
DXF OffsetX= 0
DXF OffsetY= 0
DXF ScaleX= 0
DXF ScaleY= 0

--- BUGGYBR_A.p01 (plan) ---

Plan Title=Floodplain
Program Version=5.07
Short Identifier=Floodplain
Geom File=g01
Flow File=f01
Subcritical Flow
K Sum by GR= 0
Std Step Tol= 0.01
Critical Tol= 0.01
Num of Std Step Trials= 20
Max Error Tol= 0.3
Flow Tol Ratio= 0.001
Split Flow NTrial= 30
Split Flow Tol= 0.02
Split Flow Ratio= 0.02
Log Output Level= 0
Friction Slope Method= 1
Unsteady Friction Slope Method= 2
Unsteady Bridges Friction Slope Method= 1
Parabolic Critical Depth
Global Vel Dist= 0 , 0 , 0
Global Log Level= 0
CheckData=True
Encroach Param=-1 ,0,0, 0
Mapping Interval=1HOUR
Computation Time Step Use Courant=        0
Computation Time Step Use Time Series=    0
Computation Time Step Count To Double=0
Computation Time Step Max Doubling=0
Computation Time Step Max Halving=0
Computation Time Step Residence Courant=0
Run HTab= 0
Run UNet= 0
Run Sediment= 0
Run PostProcess= 0
Run WQNet= 0
Run RASMapper= 0
UNET Theta= 0
UNET Theta Warmup= 0
UNET ZTol= 0
UNET ZSATol= 0
UNET MxIter= 0
UNET Max Iter WO Improvement= 0
UNET MaxInSteps= 0
UNET DtIC= 0
UNET DtMin= 0
UNET MaxCRTS= 0
UNET WFStab= 0
UNET SFStab= 0
UNET WFX= 1
UNET SFX= 1
UNET 1D Methodology=Finite Difference
UNET DSS MLevel= 1
UNET Pardiso=0
UNET DZMax Abort= 0
UNET Use Existing IB Tables= 0
UNET Froude Reduction=False
UNET Froude Limit= 0
UNET Froude Power= 0
UNET D1 Cores= 0
UNET D2 Coriolis=0
UNET D2 Cores= 0
UNET D2 Theta= 1
UNET D2 Theta Warmup= 1
UNET D2 Z Tol= 0.01
UNET D2 Volume Tol= 0.01
UNET D2 Max Iterations= 20
UNET D2 Equation= 0
UNET D2 RampUpFraction=0.1
UNET D2 TimeSlices= 1
UNET D2 BCVolumeCheck=0
UNET D1D2 MaxIter= 0
UNET D1D2 ZTol=0.01
UNET D1D2 QTol=0.1
UNET D1D2 MinQTol=1
Write IC File= 0
Write IC File at Fixed DateTime=0
Write IC File at Sim End=0
Echo Input=False
Echo Parameters=False
Echo Output=False
Write Detailed= 0
HDF Write Warmup=0
HDF Write Time Slices=0
HDF Flush=0
HDF Face Node Velocities=0
HDF Compression= 1
HDF Chunk Size= 1
HDF Spatial Parts= 1
HDF Use Max Rows=0
HDF Fixed Rows= 1
Calibration Method= 0
Calibration Iterations= 20
Calibration Max Change=0.05
Calibration Tolerance=0.2
Calibration Maximum=1.5
Calibration Minimum=0.5
Calibration Optimization Method= 1
WQ AD Non Conservative
WQ ULTIMATE=-1
WQ Max Comp Step=1HOUR
WQ Output Interval=15MIN
WQ Output Selected Increments= 0
WQ Output face flow=0
WQ Output face velocity=0
WQ Output face area=0
WQ Output face dispersion=0
WQ Output cell volume=0
WQ Output cell surface area=0
WQ Output cell continuity=0
WQ Output cumulative cell continuity=0
WQ Output face conc=0
WQ Output face dconc_dx=0
WQ Output face courant=0
WQ Output face peclet=0
WQ Output face adv mass=0
WQ Output face disp mass=0
WQ Output cell mass=0
WQ Output cell source sink temp=0
WQ Output nsm pathways=0
WQ Output nsm derived pathways=0
WQ Output MaxMinRange=-1
WQ Daily Max Min Mean=-1
WQ Daily Range=0
WQ Daily Time=0
WQ Create Restart=0
WQ Fixed Restart=0
WQ System Summary=0
WQ Write To DSS=0
WQ Use Fixed Temperature=0
Sorting and Armoring Iterations= 10
XS Update Threshold= 0.02
Bed Roughness Predictor= 0
Hydraulics Update Threshold= 0.02
Energy Slope Method= 1
Volume Change Method= 1
Sediment Retention Method= 0
XS Weighting Method= 0
Number of US Weighted Cross Sections= 1
Number of DS Weighted Cross Sections= 1
Upstream XS Weight=0
Main XS Weight=1
Downstream XS Weight=0
Number of DS XS's Weighted with US Boundary= 1
Upstream Boundary Weight= 1
Weight of XSs Associated with US Boundary= 0
Number of US XS's Weighted with DS Boundary= 1
Downstream Boundary Weight= 0.5
Weight of XSs Associated with DS Boundary= 0.5
Percentile Method= 0
Sediment Output Level= 3
Mass or Volume Output= 0
Output Increment Type= 1
Profile and TS Output Increment= 1
XS Output Flag= 0
XS Output Increment= 10
Write Gradation File= 0
Read Gradation Hotstart= 0
Write HDF5 File= 1
Write Binary Output= 1
Write DSS Sediment File= 0
SV Curve= 0
Specific Gage Flag= 0

--- BUGGYBR_A.f01 (steady flow) ---

Flow Title=Flows
Program Version=5.07
Number of Profiles= 6
Profile Names=01pct,10pct,04pct,02pct,0_2pct,01plus
River Rch & RM=BUGGYBR_A,Main            ,3811
     557     269     373     461     825     930
River Rch & RM=BUGGYBR_A,Main            ,3585
     639     310     428     529     942    1066
River Rch & RM=BUGGYBR_A,Main            ,0
     709     347     477     588    1038    1170
Boundary for River Rch & Prof#=BUGGYBR_A,Main            , 1
Up Type= 0
Dn Type= 1
Dn Known WS=1518.6
Boundary for River Rch & Prof#=BUGGYBR_A,Main            , 2
Up Type= 0
Dn Type= 1
Dn Known WS=1517.3
Boundary for River Rch & Prof#=BUGGYBR_A,Main            , 3
Up Type= 0
Dn Type= 1
Dn Known WS=1517.8
Boundary for River Rch & Prof#=BUGGYBR_A,Main            , 4
Up Type= 0
Dn Type= 1
Dn Known WS=1518.5
Boundary for River Rch & Prof#=BUGGYBR_A,Main            , 5
Up Type= 0
Dn Type= 1
Dn Known WS=1518.8
Boundary for River Rch & Prof#=BUGGYBR_A,Main            , 6
Up Type= 0
Dn Type= 1
Dn Known WS=1518.9
DSS Import GetInterval= 0
DSS Import GetPeak= 0
DSS Import FillOption= 0

--- BUGGYBR_A.g01 (geometry) ---

Geom Title=Geometry
Program Version=5.07

River Reach=BUGGYBR_A       ,Main
Reach XY= 30
2050510.94399999 253198.032999912050557.13099999253086.003999908
     2050617.137252809.683999919     2050662.057252729.184999912
2050688.06547153252625.8321733432050685.55399999252323.385999917
2050651.92199999252276.706999912     2050586.143252238.147999906
2050579.09991868252078.811298015     2050550.006252048.282999912
     2050499.849251932.3379999052050522.35899999251850.469999923
2050606.21399999251846.344999919     2050657.906251820.072999911
     2050630.307251707.4369999132050646.25228779251612.050170643
2050640.18099999251430.4469999152050656.34899999251186.081999913
2050634.99399999251075.6659999122050592.46899999251038.432999908
2050587.37260487250935.8094877262050486.09503777250651.255606971
2050429.44899999250573.3289999172050416.76499999250447.279999914
     2050369.032250365.5159999122050371.45299999250132.696999915
     2050333.644250083.839999917     2050355.515250027.733999904
     2050488.823249927.4949999142050562.31281523 249832.83599631

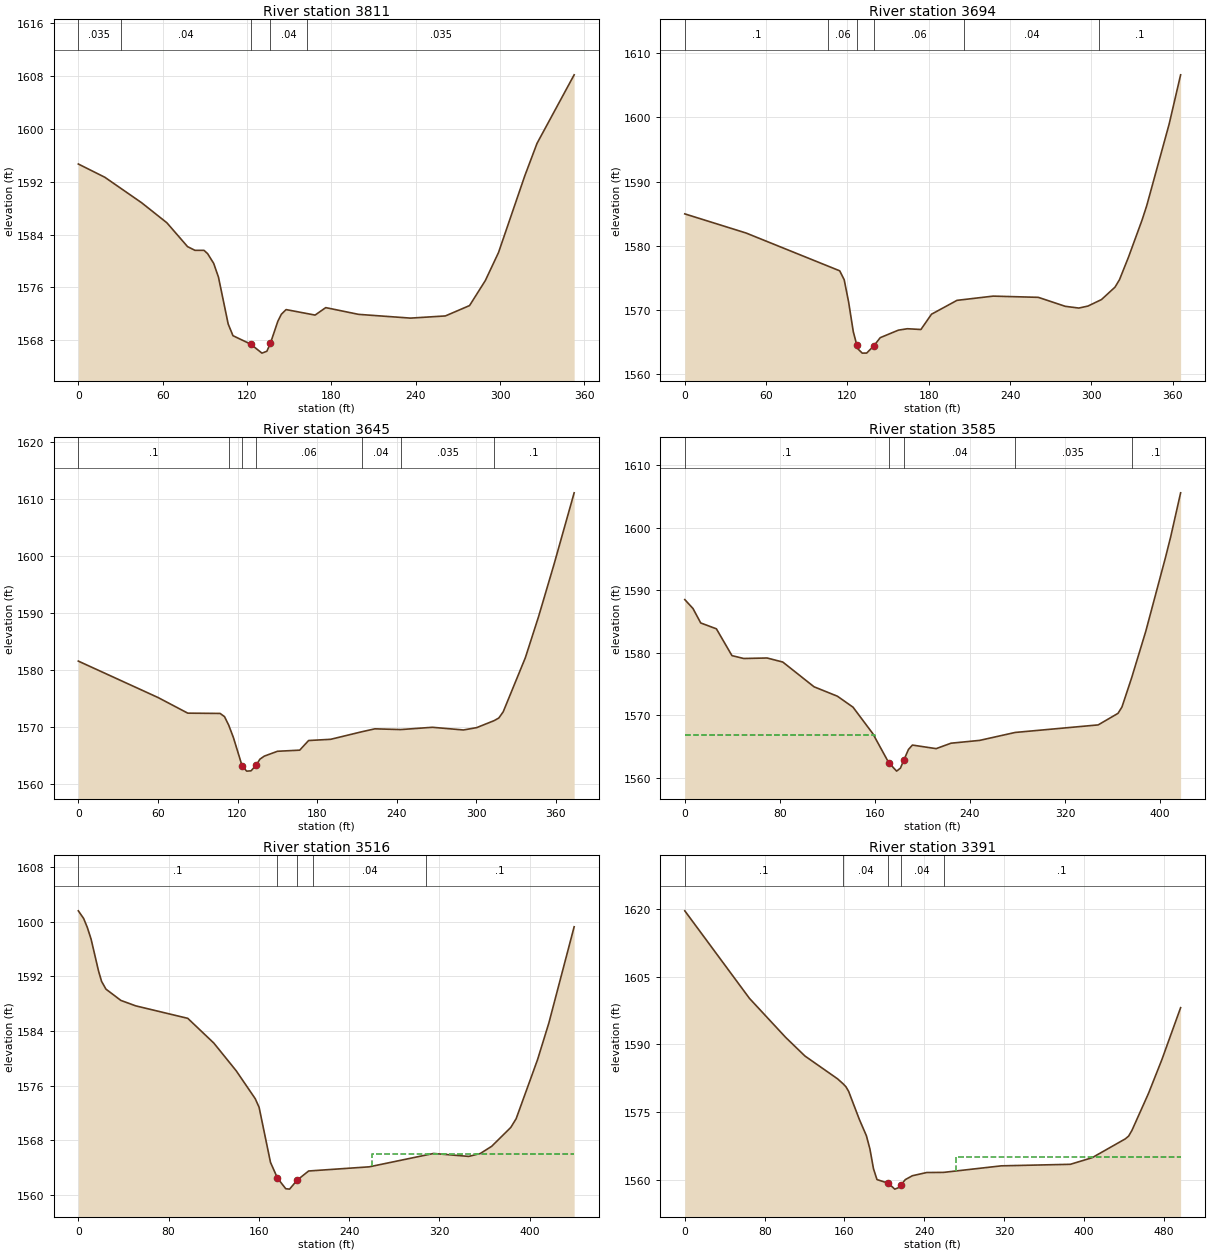
Type RM Length L Ch R = 1 ,3811    ,116.8,116.8,116.8
XS GIS Cut Line= 3
2050594.99787372253284.2275205892050557.46622619253210.250503879
2050299.75285459253130.700807895
#Sta/Elev= 30
       0 1594.68    18.8 1592.68      45 1588.82      63 1585.78    77.7 1582.17
      83 1581.61    89.4 1581.61      92  1581.1    96.3 1579.63    99.7 1577.54
   106.6 1570.46     110 1568.69   122.6 1567.41   130.6 1566.05   134.1 1566.33
   136.6 1567.52   141.9 1570.86   144.4 1571.93   147.8 1572.64   168.4 1571.81
     176 1572.94   199.3 1571.92   236.3 1571.35   261.1 1571.68   278.3 1573.25
   289.5 1577.03   298.9 1581.28   317.6  1592.9   326.3 1597.81   352.7 1608.18
#Mann= 5 ,-1 , 0
       0    .035       0      30     .04       0   122.6    .045       0
   136.6     .04       0  162.95    .035       0
Bank Sta=122.6,136.6
XS Rating Curve= 0 ,0
Exp/Cntr=0.3,0.1

Type RM Length L Ch R = 1 ,3694    ,49.4,49.6,49.7
XS GIS Cut Line= 3
2050651.33873454253171.7599654012050592.59884367253096.266325755
2050326.41057905253050.363387664
#Sta/Elev= 30
       0 1584.97    45.2 1581.99   114.3  1576.1   117.6 1574.71   120.9  1571.2
   124.3 1566.63   126.9 1564.53   127.6 1563.97   130.9 1563.28   134.2 1563.29
   139.4  1564.4   144.2 1565.69   157.6 1566.86   164.2 1567.08   174.2 1566.96
     182 1569.34   200.8  1571.5   227.5 1572.16   260.8 1571.97   280.7 1570.57
   290.7  1570.3   297.4 1570.61   307.4 1571.62   317.4 1573.56   320.7 1574.72
   327.3 1578.21   337.3 1583.98   340.7 1586.18   357.3 1598.93   365.8 1606.63
#Mann= 6 ,-1 , 0
       0      .1       0  105.65     .06       0   126.9    .045       0
   139.4     .06       0  205.65     .04       0  305.65      .1       0
Bank Sta=126.9,139.4
XS Rating Curve= 0 ,0
Exp/Cntr(USF)=0,0
Exp/Cntr=0.5,0.3

Type RM Length L Ch R = 1 ,3645    ,59.8,59.7,59.7
XS GIS Cut Line= 3
2050662.34521054253114.6431926462050611.35837842253049.814144476
2050324.75629909252997.426428942
#Sta/Elev= 30
       0 1581.62    60.2 1575.22    82.5 1572.49   106.9 1572.44   110.2 1571.88
   113.4 1570.37   116.9 1568.22   123.5 1563.22   126.9 1562.32   130.2 1562.37
   134.1 1563.38   136.9 1564.42   140.2 1564.95   150.1  1565.8   166.9    1566
   173.6 1567.69   190.2  1567.9   213.6 1569.22   223.6 1569.74   243.1 1569.61
   266.9 1570.01   290.3 1569.54   300.3 1569.95   313.5 1571.18     317 1571.64
   320.3 1572.72     337 1582.21     347 1589.45   358.6 1598.58   373.8 1611.14
#Mann= 7 ,-1 , 0
       0      .1       0   113.4     .06       0   123.5    .045       0
   134.1     .06       0   213.6     .04       0   243.1    .035       0
   313.5      .1       0
#XS Ineff= 2 , 0
       0   108.5  1566.3     149       0  1565.3
Permanent Ineff=
       F       F
Bank Sta=123.5,134.1
XS Rating Curve= 0 ,0
Exp/Cntr(USF)=0,0
Exp/Cntr=0.5,0.3

Type RM Length L Ch R = 1 ,3585    ,68.2,68.6,69.5
XS GIS Cut Line= 3
2050751.70389972252981.335799197 2050616.2715899252989.515639932
2050338.54196542252942.283763606
#Sta/Elev= 30
       0 1588.52     6.9 1587.09    13.4 1584.78    26.6 1583.84    39.7 1579.55
    49.6 1579.09    69.3 1579.17    82.5 1578.52   108.8 1574.56   128.5 1573.05
   141.6  1571.3   158.3 1567.06   171.6 1562.44   178.3 1561.06   181.5 1561.53
   184.3 1562.78   188.3 1564.53   191.6 1565.23   211.6 1564.66   224.1 1565.53
   248.2 1565.98   278.1 1567.25     348 1568.46   364.7 1570.31     368 1571.32
   376.1 1575.96     388  1583.4   404.6 1595.22     409 1598.54   417.4 1605.61
#Mann= 5 ,-1 , 0
       0      .1       0   171.6    .045       0   184.3     .04       0
   278.1    .035       0   376.1      .1       0
#XS Ineff= 2 , 0
       0  160.46 1566.92  192.32       0  1564.5
Permanent Ineff=
       F       F
Bank Sta=171.6,184.3
XS Rating Curve= 0 ,0
Exp/Cntr(USF)=0,0
Exp/Cntr=0.5,0.3

Type RM Length L Ch R = 1 ,3516    ,123.3,125.4,126.6
XS GIS Cut Line= 3
2050779.07120453252914.9716014652050641.73095849252928.323824209
2050349.01907184252856.261205682
#Sta/Elev= 30
       0 1601.63     4.7 1600.51       8 1599.18    11.3 1597.48    17.9 1592.81
    20.6 1591.28    24.5 1590.14    37.7 1588.49    50.9 1587.69      97 1585.86
   120.1 1582.23   139.9 1578.17   156.8 1574.07   160.2 1572.81   170.3 1564.73
   176.5 1562.42   183.8 1560.87   187.2 1560.81     194 1562.14   204.1 1563.47
   257.8 1564.08   314.8 1566.04     346 1565.61   356.2 1566.03   366.3 1567.09
   383.2 1569.85     388 1571.14     407 1579.82     417 1585.19   439.4 1599.29
#Mann= 5 ,-1 , 0
       0      .1       0   176.5    .045       0     194      .1       0
  207.99     .04       0  307.99      .1       0
#XS Ineff= 2 , 0
                             260            1566
Permanent Ineff=
       F       F
Bank Sta=176.5,194
XS Rating Curve= 0 ,0
Exp/Cntr(USF)=0,0
Exp/Cntr=0.3,0.1

Type RM Length L Ch R = 1 ,3391    ,210.5,206.3,201.7
XS GIS Cut Line= 4
2050832.23559007252833.8911127312050674.85028043252816.610752579
2050506.33104642252746.8664870522050352.13639164 252772.01206076
#Sta/Elev= 30
       0 1619.61    64.8 1600.21   101.1 1591.56   120.4 1587.44   153.1 1582.38
   158.8 1581.25   161.5 1580.62   164.2  1579.6   174.9  1573.4     182 1569.77
   185.5 1566.86   189.1 1562.46   192.6 1560.06   204.1 1559.23   210.4 1557.94
   213.9 1558.23   216.61558.837     221 1560.05   228.1 1560.91   242.4 1561.62
   259.4 1561.65   317.2  1563.1   386.4 1563.44   408.2  1564.9   441.4 1569.07
   444.8 1569.69   448.1 1570.95   464.7 1579.15     478 1586.57   496.9 1598.15
#Mann= 5 ,-1 , 0
       0      .1       0   158.8     .04       0   204.1    .045       0
   216.6     .04       0   259.4      .1       0
#XS Ineff= 2 , 0
       0                  271.96       0 1564.98
Permanent Ineff=
       F       F
Bank Sta=204.1,216.6
XS Rating Curve= 0 ,0
Exp/Cntr=0.3,0.1

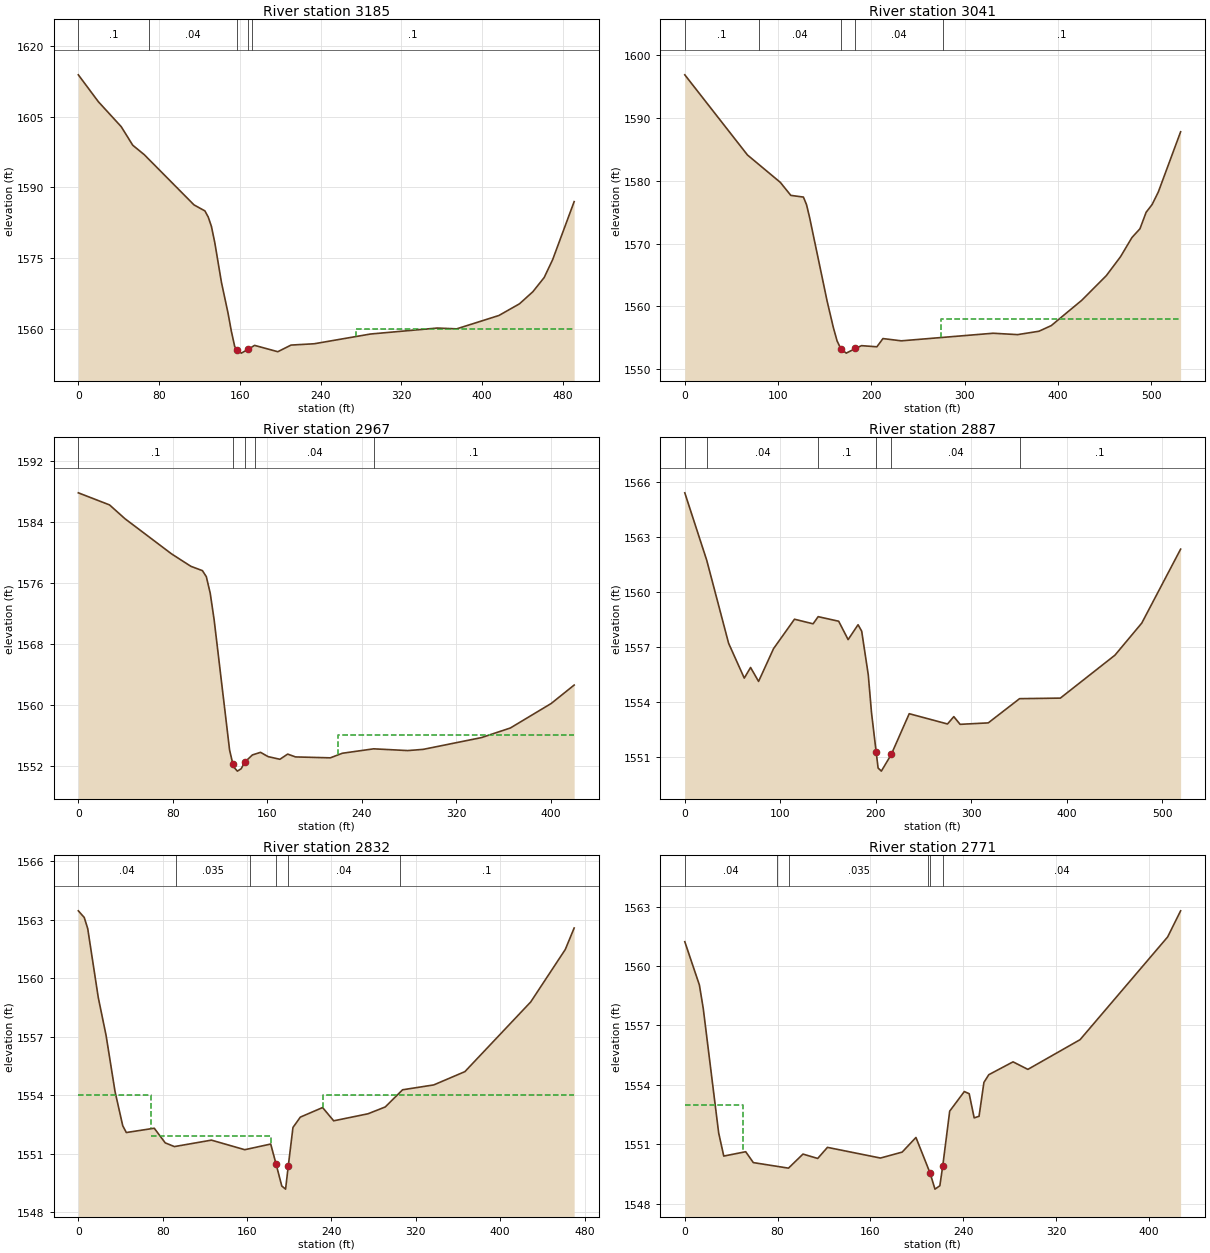
Type RM Length L Ch R = 1 ,3185    ,142.8,143.4,143.5
XS GIS Cut Line= 3
2050834.15556177252663.0282465692050728.82595223 252602.04194189
2050359.46573688252610.598042909
#Sta/Elev= 30
       0 1613.81    19.8 1608.14    42.5 1602.85    53.9 1598.93    65.3 1596.94
   114.6 1586.32   125.4 1585.05   128.7 1583.75   131.9 1581.74   135.2 1578.32
   141.8 1569.93   148.3 1563.45   151.6 1559.62   154.9 1556.41   156.8 1555.73
   161.5 1554.99     168 1555.77   174.6 1556.63   197.6 1555.29   210.7 1556.69
   233.7 1556.97   289.5 1559.03   355.6 1560.29   374.8 1560.12   416.6 1562.94
   437.1 1565.42   450.3 1567.97   461.5 1570.97   469.9 1574.75   491.2 1587.01
#Mann= 5 ,-1 , 0
       0      .1       0      70     .04       0   156.8    .045       0
     168     .04       0  171.71      .1       0
#XS Ineff= 2 , 0
                             275            1560
Permanent Ineff=
       F       F
Bank Sta=156.8,168
XS Rating Curve= 0 ,0
Exp/Cntr=0.3,0.1

Type RM Length L Ch R = 1 ,3041    ,73.7,74.1,74.1
XS GIS Cut Line= 3
2050843.76649025252518.6859471072050742.05890752252461.092496645
2050327.26352494252461.705192927
#Sta/Elev= 30
       0  1596.9    67.2 1584.12   102.4 1579.76   113.7 1577.68   127.2 1577.41
   130.5 1576.22   133.8 1574.18   152.7 1560.77   159.2 1556.67   163.3 1554.48
   167.4 1553.21   173.1 1552.53     183 1553.27   189.5 1553.72     206 1553.54
   212.5 1554.85   232.2 1554.49   330.6  1555.7   356.9 1555.48   379.8 1556.02
     393 1556.92   425.8 1560.97     452 1564.88   467.2 1567.89   479.5 1570.96
   488.1 1572.36   494.7 1574.98   501.2 1576.24   507.8 1578.23   531.7 1587.82
#Mann= 5 ,-1 , 0
       0      .1       0      80     .04       0   167.4    .045       0
     183     .04       0  276.88      .1       0
#XS Ineff= 2 , 0
                             275            1558
Permanent Ineff=
       F       F
Bank Sta=167.4,183
XS Rating Curve= 0 ,0
Exp/Cntr(USF)=0,0
Exp/Cntr=0.3,0.1

Type RM Length L Ch R = 1 ,2967    ,95,80.2,63.9
XS GIS Cut Line= 2
2050827.00873438252386.4372012852050407.15248052252390.457101588
#Sta/Elev= 30
       0 1587.77    26.4 1586.19    39.5 1584.38    78.9 1579.78    95.3 1578.15
   105.1 1577.58   108.4 1576.79   111.7 1574.62     115 1571.16   128.1 1554.09
   130.81552.298   131.4  1551.9   134.7 1551.33   137.9 1551.64     1411552.514
   147.4 1553.45   154.3 1553.79   160.7 1553.23   170.7 1552.88   177.3 1553.56
   183.9 1553.19   213.4 1553.07   223.6 1553.67   250.1 1554.25     279 1554.02
   292.1 1554.18   341.4 1555.72   365.9 1556.98   400.4 1560.18   419.9  1562.6
#Mann= 5 ,-1 , 0
       0      .1       0   130.8    .045       0     141      .1       0
     150     .04       0     250      .1       0
#XS Ineff= 2 , 0
                             220            1556
Permanent Ineff=
       F       F
Bank Sta=130.8,141
XS Rating Curve= 0 ,0
Exp/Cntr(USF)=0,0
Exp/Cntr=0.5,0.3

Type RM Length L Ch R = 1 ,2887    ,52.2,55.1,59.5
XS GIS Cut Line= 4
2050797.33678554 252183.432409542050720.03637521252183.456266033
2050662.49059236 252366.33769977  2050412.065692252366.784355359
#Sta/Elev= 30
       0  1565.4      23 1561.72    45.9  1557.2    62.3  1555.3    68.9 1555.88
    77.3 1555.12      93 1556.91   114.9 1558.51   134.4 1558.26   139.7 1558.65
   161.2  1558.4   171.1  1557.4   181.5 1558.21   185.3 1557.86   192.2 1555.48
   195.6 1553.41   200.51551.259   202.5  1550.4   205.9 1550.23   216.3 1551.14
   235.1 1553.36   275.2  1552.8   281.8  1553.2   288.4 1552.78   317.9 1552.86
   350.7 1554.18   393.4 1554.21   450.6 1556.55   478.7  1558.3   519.4 1562.33
#Mann= 6 ,-1 , 0
       0      .1       0      23     .04       0   139.7      .1       0
   200.5    .045       0   216.3     .04       0   350.7      .1       0
#XS Ineff= 2 , 0
       0     187  1552.5   233.2       0  1552.7
Permanent Ineff=
       F       F
Bank Sta=200.5,216.3
XS Rating Curve= 0 ,0
Exp/Cntr(USF)=0,0
Exp/Cntr=0.5,0.3

Type RM Length L Ch R = 1 ,2832    ,57.4,61,64
XS GIS Cut Line= 4
2050763.48438392252153.5807541052050682.14343828252166.831536585
2050617.13023585252336.9576876792050411.66866481 252342.31755475
#Sta/Elev= 30
       0 1563.45     5.6 1563.11     8.9 1562.54    18.9 1559.01    26.3 1557.07
    34.8 1554.19    42.1 1552.44    45.5 1552.09      72 1552.31    82.4 1551.56
    91.1 1551.37   126.2  1551.7   157.8 1551.21   182.4  1551.5   187.5 1550.47
   192.9 1549.35   196.5 1549.19     1991550.351   203.5 1552.35   210.5 1552.88
   231.6 1553.37   242.1 1552.69   274.6 1553.05     291  1553.4   307.4 1554.28
     337 1554.53   366.5 1555.21   428.9 1558.78   461.7 1561.47   470.1 1562.57
#Mann= 6 ,-1 , 0
       0     .04       0   92.41    .035       0  162.41     .04       0
   187.5    .045       0     199     .04       0  304.54      .1       0
#XS Ineff= 4 ,-1
       0      69    1554      69   182.71551.922  205.55  231.451551.829
   231.6   470.7    1554
Permanent Ineff=
       F       F       F       F
Bank Sta=187.5,199
XS Rating Curve= 0 ,0
Exp/Cntr(USF)=0,0
Exp/Cntr=0.5,0.3

Type RM Length L Ch R = 1 ,2771    ,158.4,165.3,170.8
XS GIS Cut Line= 4
2050750.74277138252116.0887625922050681.75929704252127.007010329
2050538.82950849252304.1803940532050408.80310363252306.661813993
#Sta/Elev= 30
       0 1561.23    12.6 1559.04    15.9 1557.86    29.2 1551.57    33.6  1550.4
    52.5 1550.62    59.1 1550.07    89.4 1549.79   101.9  1550.5   114.6 1550.28
     123 1550.84   168.7  1550.3   187.4  1550.6   199.3 1551.34   211.5 1549.54
   215.7 1548.73   219.9  1548.9   222.4  1549.9   228.4 1552.67     241 1553.66
   245.2 1553.55   249.5 1552.33   253.7 1552.41   257.9 1554.12   262.1 1554.51
     283 1555.16   295.8 1554.78   340.8 1556.28   416.3 1561.47   427.5 1562.79
#Mann= 6 ,-1 , 0
       0     .04       0   79.84      .1       0   89.84    .035       0
  209.84     .04       0   211.5    .045       0   222.4     .04       0
#XS Ineff= 2 , 0
              50    1553
Permanent Ineff=
       F       F
Bank Sta=211.5,222.4
XS Rating Curve= 0 ,0
Exp/Cntr(USF)=0,0
Exp/Cntr=0.3,0.1

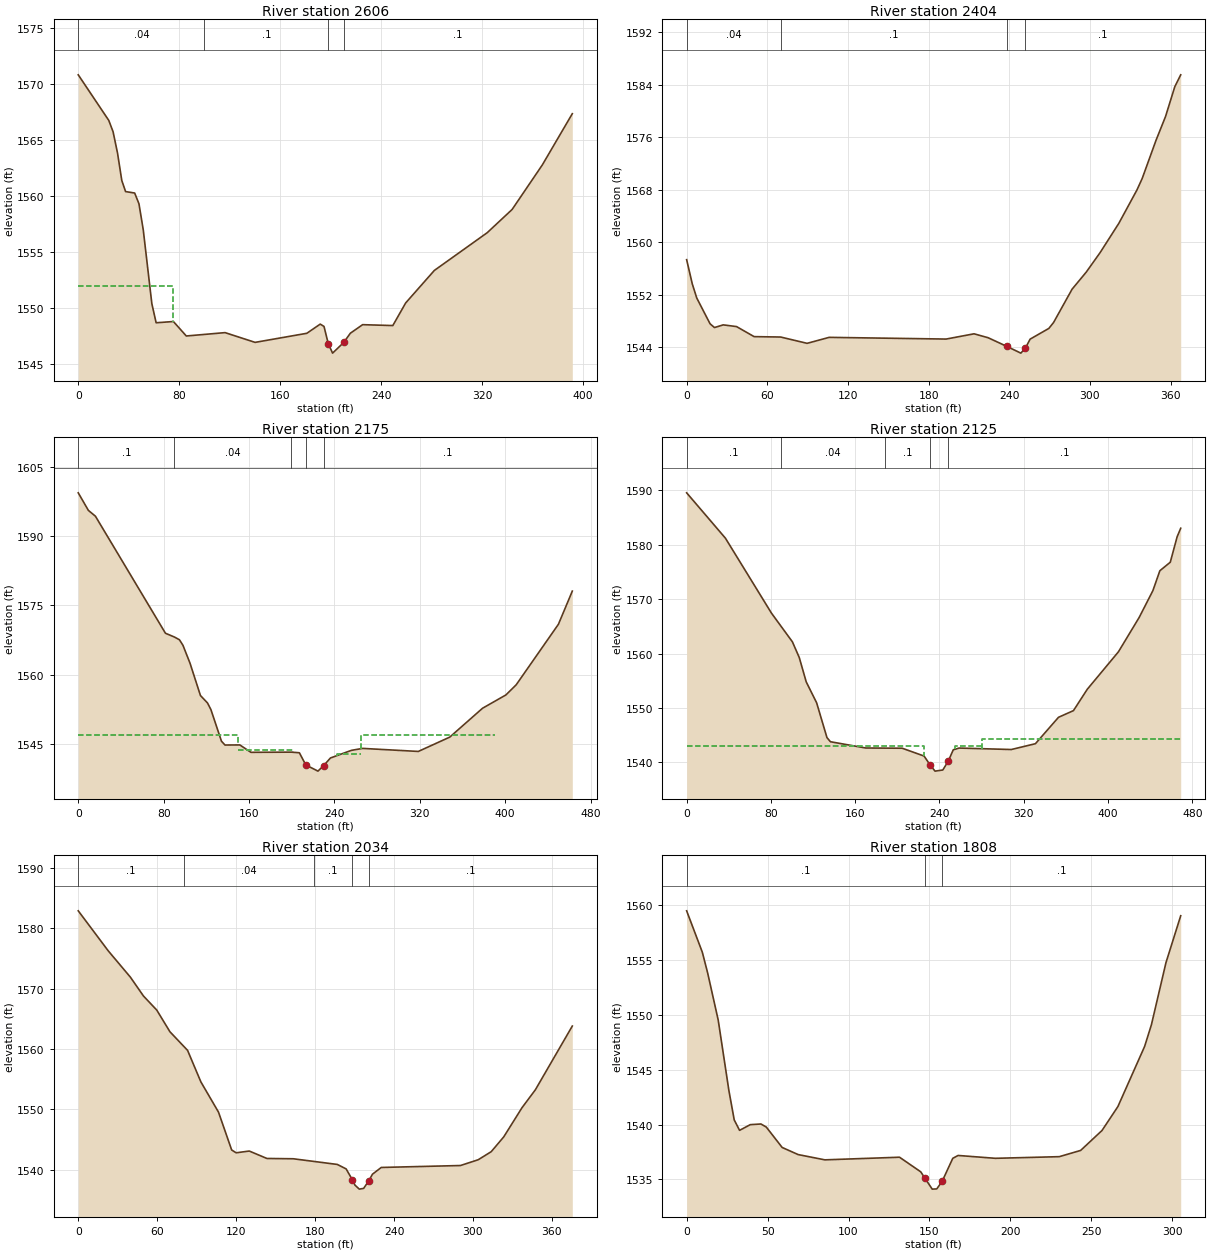
Type RM Length L Ch R = 1 ,2606    ,191.4,201.8,206.3
XS GIS Cut Line= 3
2050774.74399179252024.0986280912050466.95053267252110.842940902
2050395.38045685252109.867103607
#Sta/Elev= 30
       0 1570.82    24.2 1566.75    27.6 1565.74    31.1 1563.85    34.5 1561.39
    37.5  1560.4    44.7 1560.27    48.1 1559.31    51.5 1556.99    58.3  1550.4
    61.7 1548.69    75.4  1548.8    85.6 1547.51   116.3 1547.81   140.1 1546.94
   181.1 1547.75   191.7 1548.57   194.7 1548.36   198.1 1546.81   201.5 1545.98
   210.3 1546.93   215.6 1547.76   225.3 1548.52   249.2 1548.44   259.4 1550.46
   282.1 1553.36     324 1556.73   343.7  1558.8   367.6 1562.77   391.4 1567.35
#Mann= 4 ,-1 , 0
       0     .04       0     100      .1       0   198.1    .045       0
   210.3      .1       0
#XS Ineff= 2 , 0
              75    1552
Permanent Ineff=
       F       F
Bank Sta=198.1,210.3
XS Rating Curve= 0 ,0
Exp/Cntr=0.3,0.1

Type RM Length L Ch R = 1 ,2404    ,235.5,229.1,218
XS GIS Cut Line= 3
 2050749.1034198251928.4982780222050587.96942997 251929.45164529
2050392.89940182251862.007220663
#Sta/Elev= 30
       0 1557.36     4.2 1553.67     7.5 1551.54    17.4 1547.61    20.7 1547.03
    27.2 1547.44    37.1 1547.18    50.2 1545.65    69.9 1545.59    89.6 1544.63
     106 1545.54     193 1545.28   213.8 1546.08   224.3 1545.48   238.1 1544.17
   248.6 1543.14     252 1543.92   255.5 1545.27   269.4  1546.9   272.9 1547.79
   286.7 1552.87   297.2 1555.46   307.6 1558.45   321.5  1562.9   334.9 1567.95
   338.8 1569.69   349.2 1575.56   356.2 1579.14   363.1 1583.68   367.5 1585.49
#Mann= 4 ,-1 , 0
       0     .04       0      70      .1       0   238.1    .045       0
     252      .1       0
Bank Sta=238.1,252
XS Rating Curve= 0 ,0
Exp/Cntr(USF)=0,0
Exp/Cntr=0.5,0.3

Type RM Length L Ch R = 1 ,2175    ,49.7,50.1,49.9
XS GIS Cut Line= 4
2050869.19085123251763.7215203692050731.01844099251763.174339701
2050564.59456845251823.2316502282050416.98382932251829.743888718
#Sta/Elev= 30
       0 1599.44     9.5 1595.63    16.1 1594.37    81.7 1568.98    90.1 1568.16
    94.8 1567.57    98.1 1566.37   104.7  1562.5   114.5 1555.47   121.1 1553.86
   124.3 1552.42   134.2 1545.56   137.5 1544.73   151.4 1544.75   161.8 1543.15
   199.7 1543.19   207.2 1543.05   213.2 1540.41   224.6 1539.07     230 1540.29
   236.3 1541.92     256 1543.58   266.5    1544   318.6 1543.34   348.1 1546.45
   378.8 1552.71   400.7  1555.6   410.3 1557.79   449.9 1570.93   462.9 1578.12
#Mann= 5 ,-1 , 0
       0      .1       0    90.1     .04       0   199.7      .1       0
   213.2    .045       0     230      .1       0
#XS Ineff= 4 ,-1
       0     150    1547     150     201  1543.7     242     265  1542.7
     265     390    1547
Permanent Ineff=
       F       F       F       F
Bank Sta=213.2,230
XS Rating Curve= 0 ,0
Exp/Cntr(USF)=0,0
Exp/Cntr=0.5,0.3

Type RM Length L Ch R = 1 ,2125    ,83.8,90.4,97.2
XS GIS Cut Line= 4
 2050868.0005968251711.2914881692050710.13679591251720.710241407
2050574.54462126251766.6200945732050406.81872011251764.361947284
#Sta/Elev= 30
       0 1589.55    36.8 1581.22    80.6 1567.42   100.4 1562.17   106.9 1559.29
   113.5 1554.82   123.4 1550.96   133.2 1544.57   136.5 1543.81     170 1542.66
   204.6 1542.62   225.4 1541.18   231.3 1539.49   235.8 1538.41   243.2 1538.62
   248.4 1540.27   253.1 1542.33   258.7 1542.65   308.2 1542.38   331.1 1543.45
     353  1548.3   367.2 1549.53   380.3 1553.45   409.9 1560.34   429.6 1566.66
   442.6 1571.58   449.2 1575.23   459.1  1576.8   465.6 1581.47     469 1583.04
#Mann= 5 ,-1 , 0
       0      .1       0      90     .04       0  188.14      .1       0
   231.3    .045       0   248.4      .1       0
#XS Ineff= 3 ,-1
       0   225.3    1543   254.4     280    1543     280  469.04  1544.3
Permanent Ineff=
       F       F       F
Bank Sta=231.3,248.4
XS Rating Curve= 0 ,0
Exp/Cntr(USF)=0,0
Exp/Cntr=0.5,0.3

Type RM Length L Ch R = 1 ,2034    ,228.2,226.1,222.3
XS GIS Cut Line= 3
2050849.24236578251699.765029497 2050742.6332128251677.707963363
2050481.01190059251626.241475716
#Sta/Elev= 30
       0  1582.9    22.8 1576.27    39.6 1571.92    49.6 1568.78    59.7 1566.45
    69.7 1562.86    83.1 1559.78    93.2 1554.56   106.6 1549.55   116.6 1543.28
     120 1542.81     130  1543.1   143.4 1541.87   163.4 1541.82   196.9 1540.88
   203.6 1540.14   208.3 1538.35   210.3 1537.46   213.6 1536.79   216.9 1536.91
   220.8 1538.16   223.6 1539.26   230.3 1540.38   290.5  1540.7     304 1541.66
   313.9    1543   323.4 1545.45   337.3 1550.29   347.4 1553.24   375.5 1563.81
#Mann= 5 ,-1 , 0
       0      .1       0      80     .04       0  178.87      .1       0
   208.3    .045       0   220.8      .1       0
Bank Sta=208.3,220.8
XS Rating Curve= 0 ,0
Exp/Cntr(USF)=0,0
Exp/Cntr=0.3,0.1

Type RM Length L Ch R = 1 ,1808    ,207.6,209.9,211.1
XS GIS Cut Line= 2
2050793.85592217251423.8016202042050489.72582047251448.956639481
#Sta/Elev= 30
       0  1559.5     9.7 1555.72      13 1553.82    19.5 1549.54    26.1 1543.11
    29.4 1540.43    32.7 1539.48    39.3    1540    45.9 1540.06    49.2 1539.78
      59 1537.92    68.9 1537.27    85.4 1536.79   131.5 1537.03   144.6  1535.7
   147.1 1535.14   151.7 1534.12   154.5 1534.14   157.8 1534.82   164.4 1536.93
   167.7 1537.19   190.7 1536.93   230.2 1537.08   243.4 1537.65   256.6 1539.47
   266.4 1541.65   282.9 1547.13   287.1 1549.11   296.1 1554.78   305.2 1559.05
#Mann= 3 ,-1 , 0
       0      .1       0   147.1    .045       0   157.8      .1       0
Bank Sta=147.1,157.8
XS Rating Curve= 0 ,0
Exp/Cntr=0.3,0.1

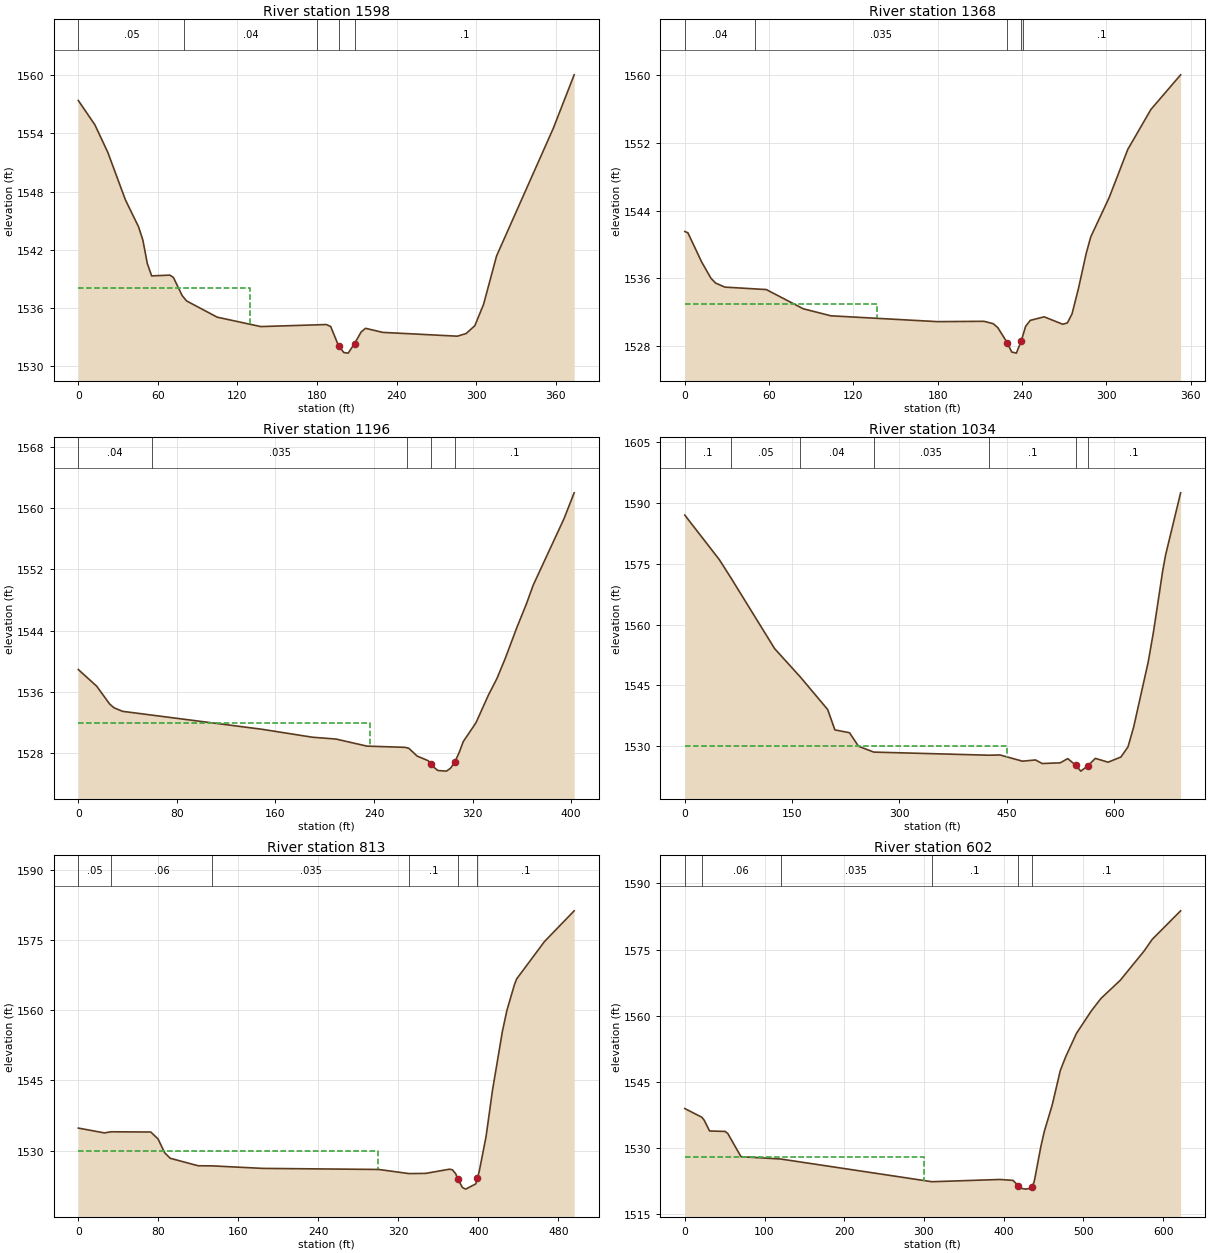
Type RM Length L Ch R = 1 ,1598    ,231.5,230.2,226.1
XS GIS Cut Line= 2
2050852.41114497251246.3789365512050479.93301818251214.030193341
#Sta/Elev= 30
       0  1557.4    12.5 1554.89    22.3 1552.03    35.5 1547.15    45.4 1544.37
    48.7 1542.98      52 1540.58    55.3  1539.3      69 1539.38    71.7 1539.14
    78.3 1537.27    81.6 1536.72   104.7 1535.04   137.6 1534.07     187 1534.28
   190.3 1534.08   196.2  1532.1   200.2 1531.39   203.5 1531.33   208.3 1532.32
   213.3 1533.52   216.6 1533.89   229.6 1533.47   285.8 1533.08   292.4 1533.35
     299 1534.16   305.6 1536.37   315.4 1541.36   358.2 1554.54   373.9 1560.05
#Mann= 5 ,-1 , 0
       0     .05       0      80     .04       0     180      .1       0
   196.2    .045       0   208.3      .1       0
#XS Ineff= 2 , 0
           129.8    1538
Permanent Ineff=
       F       F
Bank Sta=196.2,208.3
XS Rating Curve= 0 ,0
Exp/Cntr=0.3,0.1

Type RM Length L Ch R = 1 ,1368    ,172.3,172.3,169.1
XS GIS Cut Line= 3
2050822.50181499251017.7679870792050692.18138172251010.700580505
2050471.22112972251036.195994196
#Sta/Elev= 30
       0 1541.55     2.2  1541.4      12 1537.95    18.6 1536.03    21.9 1535.46
    28.5 1534.98      58 1534.69    84.3 1532.42     104 1531.59   179.9  1530.9
   212.9 1530.94   219.5 1530.66   222.8 1530.19   229.4 1528.43   232.7 1527.31
     236 1527.18   239.5 1528.64   242.6 1530.35   245.9 1531.05   255.8 1531.47
     269 1530.59   272.3 1530.75   275.6 1531.81   280.2 1534.83   285.6 1538.89
   288.9  1540.9   302.1 1545.58   315.3 1551.25   331.8 1555.98   352.9 1560.06
#Mann= 5 ,-1 , 0
       0     .04       0      50    .035       0   229.4    .045       0
   239.5    .035       0  240.51      .1       0
#XS Ineff= 2 , 0
             137    1533
Permanent Ineff=
       F       F
Bank Sta=229.4,239.5
XS Rating Curve= 0 ,0
Exp/Cntr=0.3,0.1

Type RM Length L Ch R = 1 ,1196    ,162.6,161.3,159.9
XS GIS Cut Line= 3
2050834.13613366250880.9519799092050688.52143607250823.607256979
2050451.44904223250888.822477382
#Sta/Elev= 30
       0 1538.94    14.9 1536.77    25.4 1534.45      29 1533.95      36 1533.49
   148.8 1531.16   189.9 1530.12   209.1 1529.88   234.2 1528.96   265.2  1528.8
   268.2 1528.68     275 1527.66   283.8 1527.07   286.5 1526.68   288.6  1526.2
   291.8 1525.78   298.8  1525.7   302.2  1526.1   305.6 1526.91     309 1528.09
   312.4 1529.55   322.7    1532   332.9 1535.64   339.7 1537.76   346.5  1540.4
   355.9 1544.42   363.5 1547.43   369.2 1549.95   394.1 1558.58   402.4 1561.97
#Mann= 5 ,-1 , 0
       0     .04       0      60    .035       0   266.5      .1       0
   286.5    .045       0   305.6      .1       0
#XS Ineff= 2 , 0
             237    1532
Permanent Ineff=
       F       F
Bank Sta=286.5,305.6
XS Rating Curve= 0 ,0
Exp/Cntr=0.3,0.1

Type RM Length L Ch R = 1 ,1034    ,218.1,221.3,223.1
XS GIS Cut Line= 3
2051031.47165387250640.9827557252050812.81164118250591.572970244
2050374.11886239250757.031783166
#Sta/Elev= 30
       0 1587.06    48.3 1576.05    65.1 1571.38   125.6 1554.07   161.4 1547.09
   199.7 1539.04   209.8    1534   230.2 1533.31   242.8 1529.96   264.2 1528.52
   425.1 1527.75   440.6 1527.81     472 1526.28   490.2 1526.58   499.5  1525.7
   524.7 1525.87   535.2 1526.91   546.31525.309   553.4 1523.82   563.21525.088
   573.8 1526.97   591.6 1526.03   609.5  1527.3   619.4 1529.79   627.3 1534.66
   647.7 1550.78   655.3 1558.47     668 1573.34     672 1577.21     693 1592.56
#Mann= 7 ,-1 , 0
       0      .1       0    65.1     .05       0   161.4     .04       0
   264.2    .035       0   425.1      .1       0   546.3    .045       0
   563.2      .1       0
#XS Ineff= 2 , 0
       0     450    1530               0
Permanent Ineff=
       F       F
Bank Sta=546.3,563.2
XS Rating Curve= 0 ,0
Exp/Cntr(USF)=0,0
Exp/Cntr=0.3,0.1

Type RM Length L Ch R = 1 ,813     ,205.9,210.9,211.6
XS GIS Cut Line= 3
2050803.30509014250435.742108339 2050386.3335665250518.228714872
2050337.16658094 250568.90853075
#Sta/Elev= 30
       0  1534.8    26.1 1533.77    32.8 1534.01    72.4 1533.96    79.7 1532.49
    86.3 1529.53    91.9 1528.35   119.8 1526.75   133.8 1526.73   184.1 1526.19
   300.4 1525.96   330.5 1525.08   347.2 1525.12   371.1 1526.02     374 1525.89
   377.3 1525.04   379.5 1523.87     384 1522.11   387.3 1521.76   397.4 1522.89
     399 1524.16   400.7 1525.44   407.6 1532.96   414.1 1542.93     424 1555.51
   428.5 1559.97   435.9 1565.37   438.2 1566.66     466 1574.64   495.7 1581.21
#Mann= 6 ,-1 , 0
       0     .05       0    32.8     .06       0   133.8    .035       0
   330.5      .1       0   379.5    .045       0     399      .1       0
#XS Ineff= 2 , 0
       0     300    1530               0
Permanent Ineff=
       F       F
Bank Sta=379.5,399
XS Rating Curve= 0 ,0
Exp/Cntr(USF)=0,0
Exp/Cntr=0.3,0.1

Type RM Length L Ch R = 1 ,602     ,113.7,115.4,115.8
XS GIS Cut Line= 3
 2050792.3496372250326.4208581322050326.87900569250316.358294431
2050175.75682008250356.621282994
#Sta/Elev= 30
       0 1538.93    21.3 1536.97    24.5 1536.24    31.1 1533.84    50.8 1533.74
    54.1 1533.22    70.5 1528.01   120.4 1527.48     310 1522.33   395.5 1522.84
   411.8 1522.63   418.3 1521.45   421.6 1520.85   427.4 1520.65   434.7 1520.86
   435.7 1521.24     438 1522.18   439.1 1523.07   446.6 1530.25   451.1  1533.8
     461  1539.8     471 1547.52   477.8 1550.67   491.4 1556.01   510.1 1561.12
   522.1 1563.92   546.3 1568.04   576.3  1574.7   586.4 1577.33     622 1583.79
#Mann= 6 ,-1 , 0
       0     .05       0    21.3     .06       0   120.4    .035       0
     310      .1       0   418.3    .045       0   435.7      .1       0
#XS Ineff= 2 , 0
             300    1528
Permanent Ineff=
       F       F
Bank Sta=418.3,435.7
XS Rating Curve= 0 ,0
Exp/Cntr(USF)=0,0
Exp/Cntr=0.3,0.1