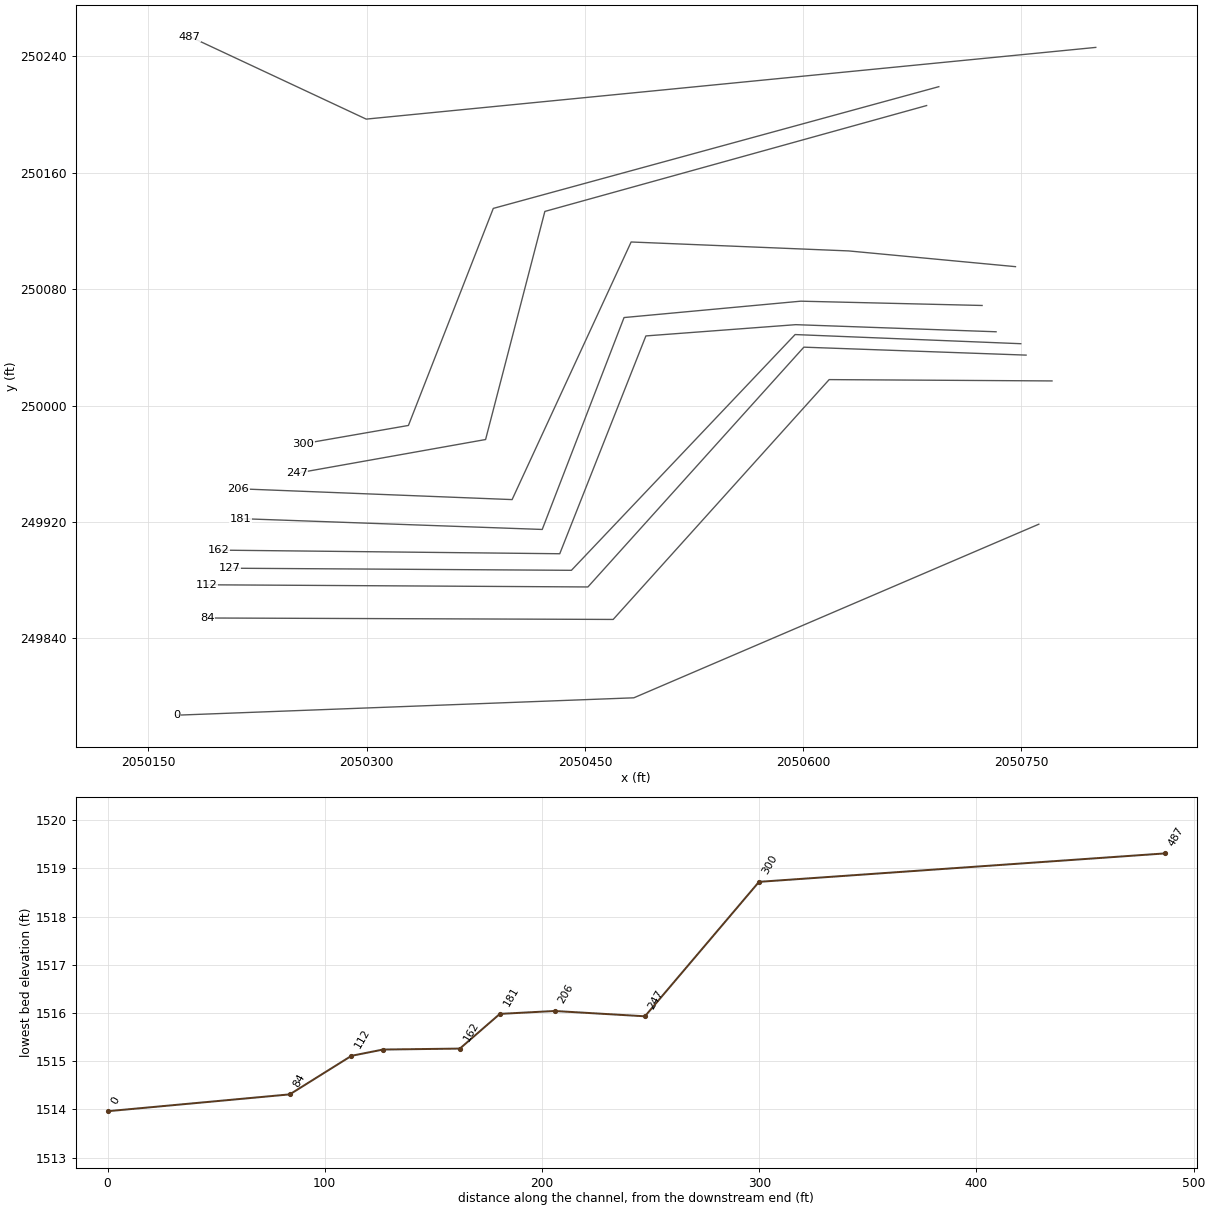
HEC-RAS study BUGGYBR_A.prj: BUGGYBR_A

--- BUGGYBR_A.g01 (geometry) --- (continued)

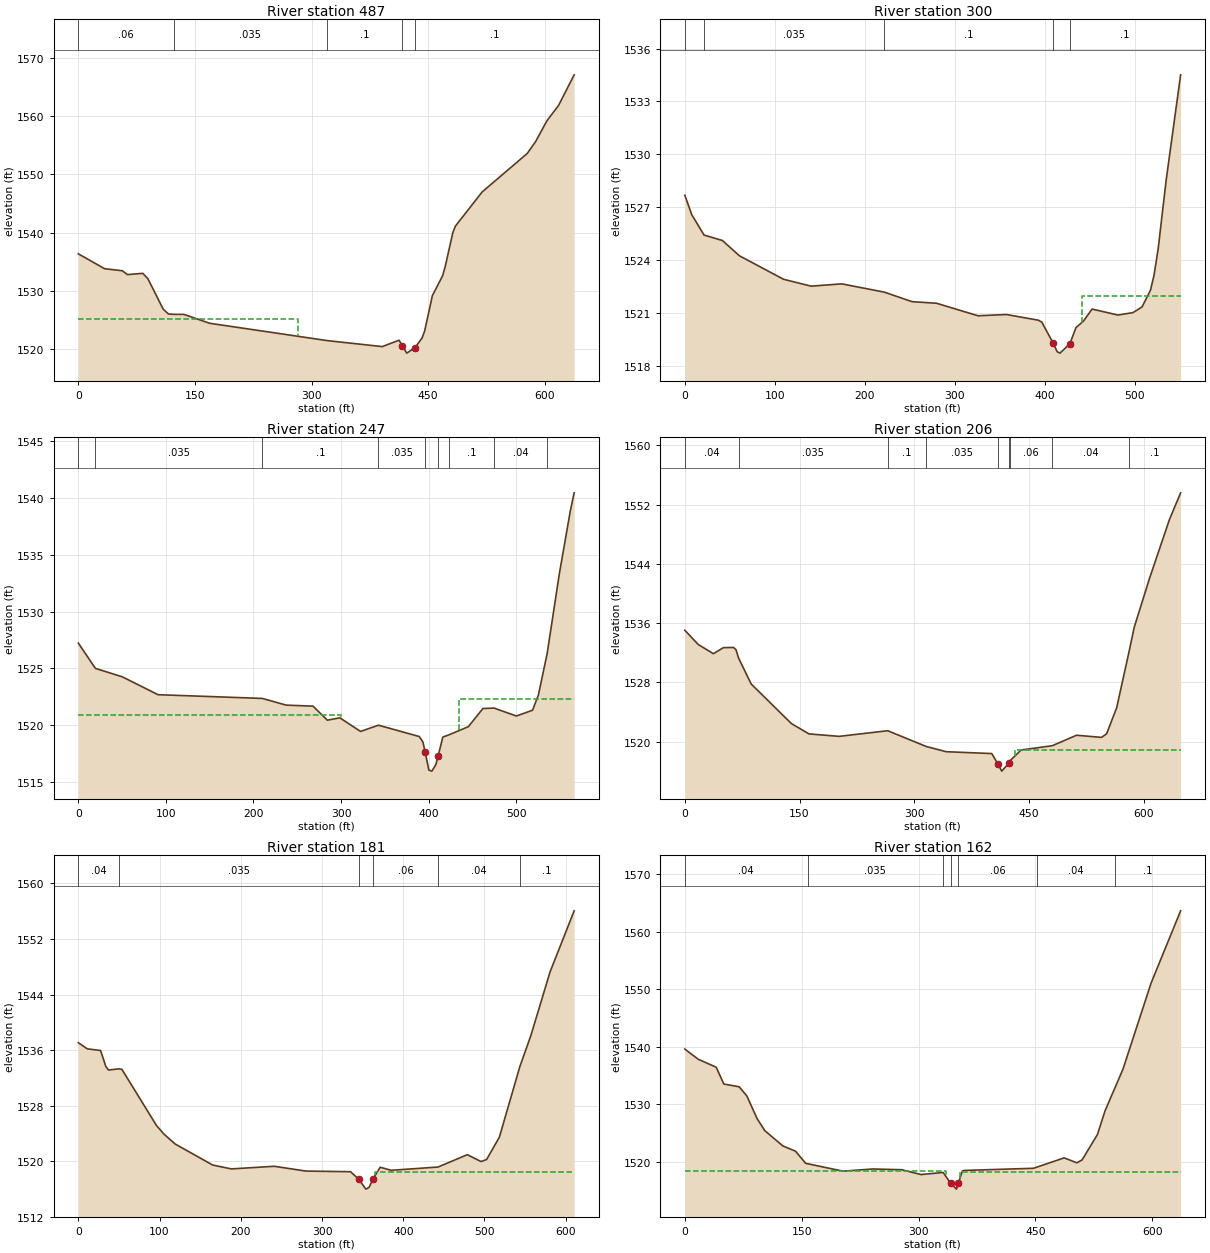
Type RM Length L Ch R = 1 ,487     ,174.7,186.9,174.7
XS GIS Cut Line= 3
 2050801.1632902250246.1792506612050299.66134923 250196.88934069
2050178.31784423250253.658351815
#Sta/Elev= 30
       0 1536.37    33.8 1533.81    56.6 1533.46    63.2  1532.8      83 1533.01
    89.5 1532.09   109.3 1526.84   115.9 1526.04   122.5 1525.97   135.7 1525.97
   168.9 1524.44   320.3 1521.46     391 1520.43   412.6 1521.53     417 1520.55
   422.5 1519.31   433.1 1520.24   442.3 1521.92   445.6 1523.14   455.5 1529.18
   468.7 1532.61     472 1534.17   481.8 1540.01   485.1 1541.12   519.5 1546.99
   577.5  1553.6   588.4 1555.66   602.8  1559.2     618 1561.89   637.9 1567.11
#Mann= 5 ,-1 , 0
       0     .06       0   122.5    .035       0   320.3      .1       0
     417    .045       0   433.1      .1       0
#XS Ineff= 2 , 0
          282.61 1525.16
Permanent Ineff=
       F       F
Bank Sta=417,433.1
XS Rating Curve= 0 ,0
Exp/Cntr(USF)=0,0
Exp/Cntr=0.5,0.3

Type RM Length L Ch R = 1 ,300     ,52.5,52.5,52.5
XS GIS Cut Line= 4
 2050693.2775224250219.1894543712050387.02865253250135.513473271
 2050328.6959046249986.3193461472050256.31237378249973.718164668
#Sta/Elev= 30
       0 1527.68     7.8 1526.57    21.4 1525.42    41.8 1525.11    60.8 1524.24
   109.8 1522.91   140.4 1522.52   174.4 1522.65   221.8 1522.18   252.6 1521.64
   279.8 1521.55   325.9 1520.84   357.6 1520.91   392.8 1520.59   396.8 1520.48
   409.4 1519.29   413.9  1518.8     417 1518.72     428 1519.25   434.8 1520.17
     443 1520.53   452.7 1521.22   481.5 1520.88   498.2 1521.02   508.2 1521.34
   517.6 1522.29   521.5 1523.13   526.1 1524.62   535.1 1528.56   551.1 1534.51
#Mann= 5 ,-1 , 0
       0     .06       0    21.4    .035       0   221.8      .1       0
   409.4    .045       0     428      .1       0
#XS Ineff= 2 , 0
       0     300 1520.97     441       0 1521.96
Permanent Ineff=
       F       F
Bank Sta=409.4,428
XS Rating Curve= 0 ,0
Exp/Cntr(USF)=0,0
Exp/Cntr=0.5,0.3

Type RM Length L Ch R = 1 ,247     ,45.3,41.6,40.8
XS GIS Cut Line= 4
2050684.88644592250206.2102202922050422.47213887250133.430813655
2050381.73808711249976.648671989 2050251.9166128249953.497664154
#Sta/Elev= 30
       0 1527.22    19.5 1524.99    50.1 1524.25      91 1522.67   210.1 1522.34
   237.4 1521.75     268 1521.66   284.4 1520.42   298.6 1520.63   322.3 1519.43
   342.7 1519.98   389.3 1518.98   393.5  1518.5     396 1517.63   400.3 1516.02
   403.7 1515.93   408.2 1516.49   410.9 1517.27   416.2 1518.93   423.5 1519.14
   445.4 1519.85     462 1521.45   474.7 1521.49   500.2 1520.79   518.7  1521.3
   525.4 1522.65   535.4 1526.31   549.3 1533.34     562 1538.95   566.2 1540.47
#Mann= 9 ,-1 , 0
       0     .06       0    19.5    .035       0   210.1      .1       0
   342.7    .035       0     396    .045       0   410.9    .035       0
   423.5      .1       0   474.7     .04       0   535.4      .1       0
#XS Ineff= 2 , 0
       0     300  1520.9     435       0  1522.3
Permanent Ineff=
       F       F
Bank Sta=396,410.9
XS Rating Curve= 0 ,0
Exp/Cntr(USF)=0,0
Exp/Cntr=0.5,0.3

Type RM Length L Ch R = 1 ,206     ,24,25.2,26
XS GIS Cut Line= 5
2050745.96397332 250095.471964312050631.31961161250106.286640347
2050481.78278113250112.4289861592050399.95514872249935.357412418
2050211.86351726249942.801672238
#Sta/Elev= 30
       0 1535.05    17.6 1533.12    37.4 1531.88    50.5  1532.7    63.7 1532.72
      67  1532.4    70.3 1531.29    86.8 1527.79   139.4 1522.45   162.4 1521.06
   201.8 1520.73   265.2 1521.49   315.4 1519.37   341.6 1518.66   401.2 1518.41
   409.5 1516.97   414.3 1516.04   423.4 1517.08   425.1 1517.44   439.6 1518.89
   480.4 1519.47     512 1520.88   544.8 1520.59   551.4 1521.08   564.5 1524.59
   580.4 1532.01   587.5 1535.46   607.2 1541.96   633.5 1549.98   648.1 1553.58
#Mann= 9 ,-1 , 0
       0     .04       0    70.3    .035       0   265.2      .1       0
   315.4    .035       0   409.5    .045       0   423.4    .035       0
   425.1     .06       0   480.4     .04       0   580.4      .1       0
#XS Ineff= 2 , 0
       0     401  1518.4   431.4       0  1518.9
Permanent Ineff=
       F       F
Bank Sta=409.5,423.4
XS Rating Curve= 0 ,0
Exp/Cntr(USF)=0,0
Exp/Cntr=0.5,0.3

Type RM Length L Ch R = 1 ,181     ,19.3,18.4,17.7
XS GIS Cut Line= 5
2050723.01657255 250068.790330672050598.33957791250071.738277489
 2050476.9073409 250060.486476962050420.66206213249914.830133957
2050213.21535514249922.274393777
#Sta/Elev= 30
       0 1537.07      11 1536.18    27.4 1535.94    33.9 1533.63    37.2 1533.13
    50.4  1533.3    53.6 1533.23    96.3 1525.13   105.5 1523.89   119.3 1522.47
   165.4 1519.45   188.4 1518.89   241.2 1519.27   280.1 1518.58   335.1 1518.49
   345.2  1517.4     354 1515.98   357.9 1516.23     363 1517.48   371.6 1519.13
   385.2 1518.69   442.8 1519.16   478.9 1520.94   495.8 1519.95   502.6 1520.24
   518.3 1523.45   543.5  1533.6   557.1 1538.09   580.7 1547.24   610.4 1556.05
#Mann= 6 ,-1 , 0
       0     .04       0    50.4    .035       0   345.2    .045       0
     363     .06       0   442.8     .04       0   543.5      .1       0
#XS Ineff= 2 , 0
       0  338.85  1517.9  365.44       0  1518.5
Permanent Ineff=
       F       F
Bank Sta=345.2,363
XS Rating Curve= 0 ,0
Exp/Cntr(USF)=0,0
Exp/Cntr=0.5,0.3

Type RM Length L Ch R = 1 ,162     ,39,35.4,31.5
XS GIS Cut Line= 5
2050732.63595445250050.7139033412050594.97498915250055.597043165
2050491.92516238250047.8599998862050432.70989193249898.136113316
2050198.46384958249900.617533257
#Sta/Elev= 30
       0  1539.6    17.3 1537.82    40.3 1536.44    50.1 1533.52    69.8 1533.04
    79.7 1531.44    92.8 1527.51   102.7 1525.42   125.7 1522.78   142.1 1521.85
   155.2 1519.74   203.1 1518.38   241.1 1518.76   278.7 1518.63   303.2 1517.79
   331.6 1518.16   341.1 1516.29   348.7 1515.26   351.2 1516.35   356.3 1518.41
   358.8 1518.51   447.6 1518.88   486.9 1520.69   503.3 1519.83   509.9 1520.33
   529.6 1524.74   539.4 1528.86   562.4  1536.1   598.5 1551.06   636.4 1563.61
#Mann= 7 ,-1 , 0
       0     .04       0  157.75    .035       0  331.09     .06       0
   341.1    .045       0   351.2     .06       0   452.1     .04       0
   552.1      .1       0
#XS Ineff= 2 , 0
          334.81 1518.35   353.5          1518.3
Permanent Ineff=
       F       F
Bank Sta=341.1,351.2
XS Rating Curve= 0 ,0
Exp/Cntr(USF)=0,0
Exp/Cntr=0.5,0.3

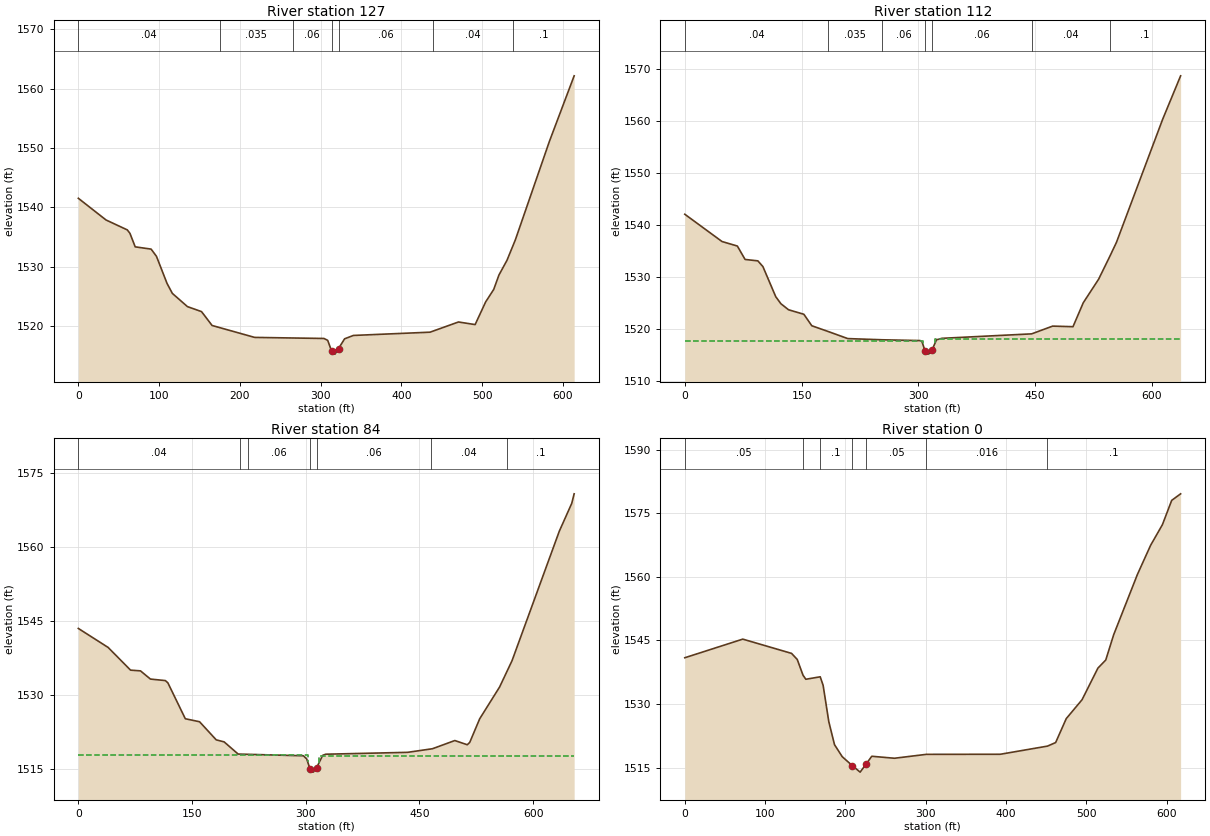
Type RM Length L Ch R = 1 ,127     ,14.3,14.5,14.7
XS GIS Cut Line= 4
2050749.60963324250042.5080773822050594.48981505  250048.7968538
2050440.73652362249886.741767696 2050205.5723559249888.188931805
#Sta/Elev= 30
       0 1541.52    34.3 1537.86    60.6 1536.19    63.9 1535.61    70.4 1533.33
    90.1 1532.95    96.7 1531.74   109.8 1527.17   116.4 1525.48   135.1 1523.25
   152.5 1522.41   165.6 1520.07   218.3 1518.06   304.1 1517.88   308.7 1517.56
   313.61515.745   317.8 1515.24   322.11516.176   329.6 1517.82   340.5 1518.39
   435.4 1518.94   470.6 1520.66   491.2 1520.22   504.3 1524.06   514.2 1526.14
   520.7 1528.58   530.6 1531.05   540.9 1534.47   583.2 1551.13   613.8 1562.17
#Mann= 7 ,-1 , 0
       0     .04       0  175.25    .035       0  265.25     .06       0
   313.6    .045       0   322.1     .06       0  438.63     .04       0
  538.63      .1       0
Bank Sta=313.6,322.1
XS Rating Curve= 0 ,0
Exp/Cntr(USF)=0,0
Exp/Cntr=0.5,0.3

Type RM Length L Ch R = 1 ,112     ,27.9,28.4,27.9
XS GIS Cut Line= 4
2050753.26357256250034.6675449762050600.50852875250040.130024343
2050452.06496746249875.3070498672050190.02702179249876.795901832
#Sta/Elev= 30
       0 1542.03    47.8 1536.78    67.5 1535.91    77.4 1533.33    93.8 1533.06
   100.3 1531.96   116.8 1526.16   123.4 1524.81   133.2 1523.65   152.9 1522.78
   163.1 1520.57   183.8 1519.48   209.3  1518.1   253.5 1517.87   302.3 1517.72
   304.6  1517.5   308.71515.655   313.2 1515.11   317.6 1515.95   323.2 1517.86
   330.1 1518.15   445.4 1519.01   472.3  1520.5   498.5 1520.39   511.7    1525
   531.4 1529.53   545.7  1533.9   554.3 1536.62   613.4 1560.22   636.7 1568.67
#Mann= 7 ,-1 , 0
       0     .04       0   183.8    .035       0   253.5     .06       0
   308.7    .045       0   317.6     .06       0   445.4     .04       0
   545.7      .1       0
#XS Ineff= 2 , 0
       0  305.54  1517.6  321.65       0 1517.94
Permanent Ineff=
       F       F
Bank Sta=308.7,317.6
XS Rating Curve= 0 ,0
Exp/Cntr(USF)=0,0
Exp/Cntr=0.5,0.3

Type RM Length L Ch R = 1 ,84      ,83.9,83.9,83.9
XS GIS Cut Line= 4
2050771.07861615250016.9239479882050617.89414407250017.832497505
2050469.43490704249852.9742704062050190.52330577249853.966838383
#Sta/Elev= 30
       0 1543.43    39.3 1539.58    68.9 1534.98      82 1534.83    95.1 1533.17
   114.8 1532.86   118.1 1532.41   141.1 1525.13   159.9 1524.52   181.9 1520.85
   192.3 1520.44   210.8 1517.97   296.9 1517.62   301.2 1516.99   305.6 1514.97
     310 1514.31   314.4 1515.23   322.3 1517.71   326.3 1517.94   434.3 1518.32
   467.1 1519.05   496.6 1520.71     513 1519.86   516.3 1520.34   529.4 1525.12
   555.7 1531.57   572.1 1536.91   634.4 1563.13   650.8 1568.77     654 1570.71
#Mann= 7 ,-1 , 0
       0     .04       0  213.19    .035       0  223.19     .06       0
   305.6    .045       0   314.4     .06       0  465.04     .04       0
  565.04      .1       0
#XS Ineff= 2 , 0
          302.38 1517.72  317.34         1517.48
Permanent Ineff=
       F       F
Bank Sta=305.6,314.4
XS Rating Curve= 0 ,0
Exp/Cntr(USF)=0,0
Exp/Cntr=0.5,0.3

Type RM Length L Ch R = 1 ,0       ,160.4,160.6,154.4
XS GIS Cut Line= 3
2050762.01464717249918.444282054 2050483.6360597249799.108803732
 2050169.4654475249787.162722339
#Sta/Elev= 30
       0 1540.92    72.2 1545.31   132.9 1541.95     140 1540.52   147.2  1536.8
   150.7 1535.85   168.6 1536.43   172.2 1534.43   179.3 1525.84   186.4 1520.43
     196  1517.6   208.5  1515.5   218.3 1513.96     226 1515.94   232.8  1517.7
     261 1517.23   300.7 1518.15   392.8 1518.17   451.5 1520.09   461.7 1520.93
   474.9 1526.57   494.6 1531.03   514.3 1538.47   524.1 1540.39     534 1546.37
   563.5 1560.55   579.9 1567.41   594.6 1572.28   606.2 1578.02   617.3 1579.56
#Mann= 7 ,-1 , 0
       0     .05       0   147.2    .016       0   168.6      .1       0
   208.5    .045       0     226     .05       0   300.7    .016       0
   451.5      .1       0
Bank Sta=208.5,226
XS Rating Curve= 0 ,0
Exp/Cntr(USF)=0,0
Exp/Cntr=0.3,0.1
LCMann Table=0

Chan Stop Cuts=-1
Use User Specified Reach Order=0
Composite Channel Slope=5